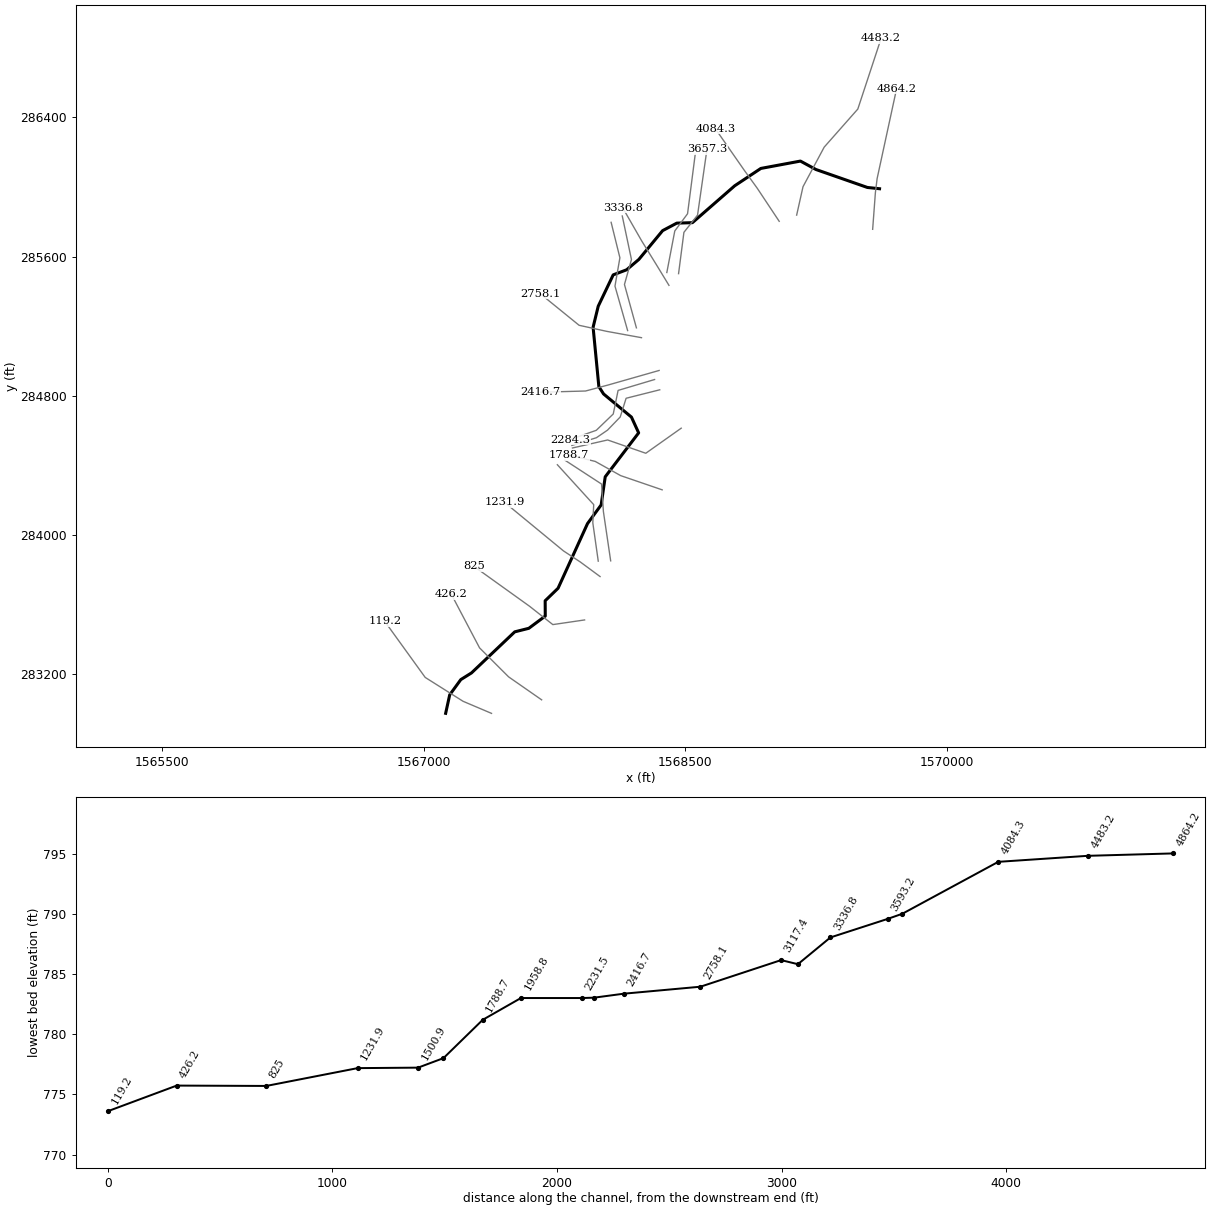
--- DTSNRN.prj (project) ---

Proj Title=DTSNRN
Current Plan=p01
Default Exp/Contr=0,0
English Units
Geom File=g01
Flow File=f01
Plan File=p01
BEGIN DESCRIPTION:
END DESCRIPTION:
DSS Export Rating Curves= 0
DSS Export Rating Curve Sorted= 0
DSS Export Volume Flow Curves= 0
DXF OffsetX= 0
DXF OffsetY= 0
DXF ScaleX= 0
DXF ScaleY= 0

--- DTSNRN.p01 (plan) ---

Plan Title=Floodplain
Program Version=4.00
Geom File=g01
Flow File=f01
K Sum by GR=0
Std Step Tol=0.01
Critical Tol=0.01
Num of Std Step Trials=20
Max Error Tol=0.3
Flow Tol Ratio=0.001
Split Flow NTrial=30
Split Flow Tol=0.02
Split Flow Ratio=0.02
Log Output Level=0
Friction Slope Method=1
Unsteady Friction Slope Method=2
Unsteady Bridges Friction Slope Method=1
Global Log Level=0
CheckData=False
Run HTab=0
Run UNet=0
Run PostProcess=0
UNET Theta=0
UNET Theta Warmup=0
UNET ZTol=0
UNET ZSATol=0
UNET MxIter=0
UNET MaxInSteps=0
UNET DtIC=0
UNET DtMin=0
UNET MaxCRTS=0
UNET WFStab=0
UNET SFStab=0
UNET WFX=0
UNET SFX=0
UNET DSS MLevel=0
UNET DZMax Abort=0
UNET Convert EG Bridges=0
UNET Use Existing IB Tables=0
UNET Froude Limit=0
UNET Froude Power=0
Write IC File=0
Echo Input=False
Echo Output=False
Write Detailed=0

--- DTSNRN.f01 (steady flow) ---

Flow Title=NFF Regression Equation
Program Version=4.10
Number of Profiles= 1
Profile Names=P100yr
River Rch & RM=DTSNRN,Main            ,4864.2
1372.329
River Rch & RM=DTSNRN,Main            ,4483.2
1373.977
River Rch & RM=DTSNRN,Main            ,4084.3
1557.273
River Rch & RM=DTSNRN,Main            ,3192.3
1583.323
River Rch & RM=DTSNRN,Main            ,119.2
1696.932
Boundary for River Rch & Prof#=DTSNRN,Main            , 1
Up Type= 0
Dn Type= 3
Dn Slope=0.00687
DSS Import GetInterval= 0
DSS Import GetPeak= 0
DSS Import FillOption= 0

--- DTSNRN.g01 (geometry) ---

Geom Title=USGS 10m DEM
Program Version=4.10

River Reach=DTSNRN          ,Main
Reach XY= 30
     1569614.039      285990.582     1569544.248      285997.874
     1569249.456      286100.998     1569160.393      286149.436
      1568933.48      286107.228     1568783.831      286007.769
     1568541.036      285795.626     1568451.527      285792.942
     1568370.307      285749.886     1568233.623       285584.08
     1568164.039      285524.957     1568086.956       285495.79
     1568001.018      285315.582      1567971.66      285194.724
     1568004.664      284853.603     1568031.747      284811.415
     1568191.454      284678.556     1568232.789      284587.978
     1568041.122      284335.374     1568017.809      284173.956
      1567939.56      284066.623      1567770.77      283695.193
     1567696.852      283623.394     1567697.372      283535.374
     1567603.102      283465.061     1567522.372      283444.748
     1567274.456      283208.811     1567212.997      283170.269
     1567149.456      283082.769     1567126.256      282976.649

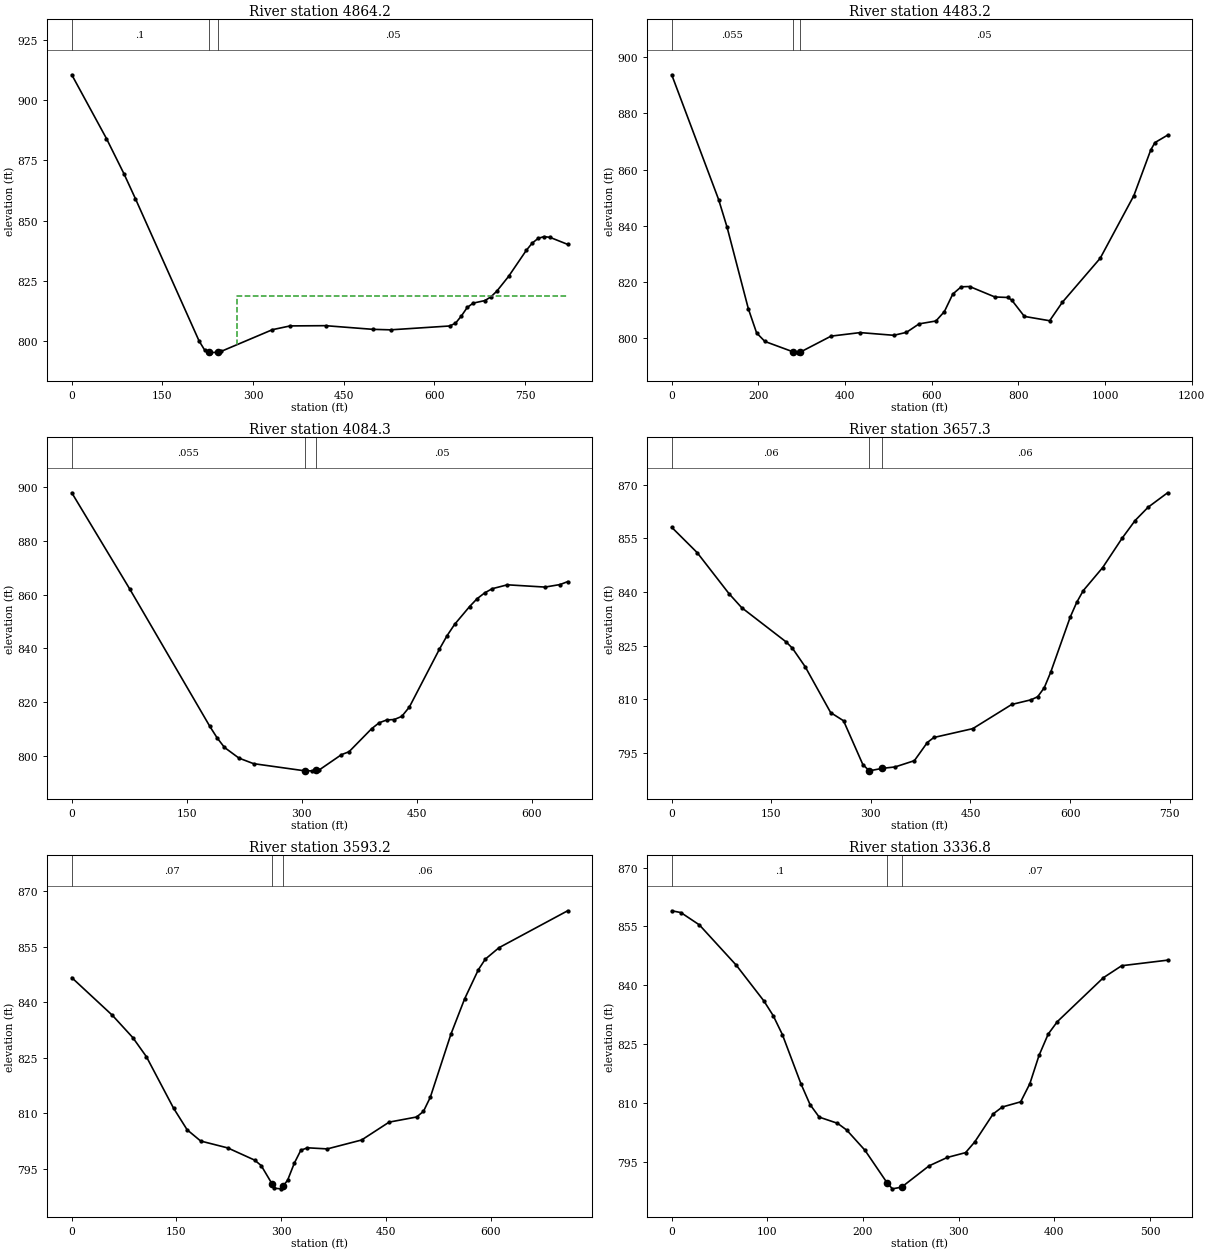
Type RM Length L Ch R = 1 ,4864.2  ,389.1,381,372.5
XS GIS Cut Line= 4
     1569574.485      285757.449      1569590.11      285967.518
     1569600.129      286049.164     1569711.638       286564.74
#Sta/Elev= 30
       0  910.58    57.4  884.07    86.2  869.51   105.3  859.08   210.6  799.97
   219.8  796.18   226.7  795.29   228.9  795.01   241.7  795.32   247.2  795.62
     332  804.64   361.3   806.2   419.9   806.3     498  804.78   527.4  804.57
     625  806.17   634.8  807.29   644.6  810.34   654.3  813.88   664.1  815.67
   683.6  816.74   693.4  818.28   703.2  820.64   722.7  826.78     752  837.61
   761.8  840.62   771.6  842.59   781.3  843.31   791.1  843.02   820.4  840.09
#Mann= 3 , 0 , 0
       0      .1       0   226.7    .045       0   241.7     .05       0
#XS Ineff= 2 , 0
                          272.58          818.57
Permanent Ineff=
       F       F
Bank Sta=226.7,241.7
XS Rating Curve= 0 ,0
Exp/Cntr=0.3,0.1

Type RM Length L Ch R = 1 ,4483.2  ,372.6,399,423.7
XS GIS Cut Line= 5
     1569138.721      285839.046      1569175.18       286002.24
     1569296.707      286229.671     1569489.416      286448.421
     1569623.096      286854.671
#Sta/Elev= 30
       0  893.72   108.2  849.35   127.9  839.41   176.8   810.5   195.9  801.89
     215  798.86   280.5  795.14   291.4  794.81   295.5  794.97   367.8  800.76
   434.8  802.01   512.5  801.05   541.7   802.1   570.8  805.11   609.7  806.14
   629.2  809.48   648.6  815.72     668   818.3   687.5   818.4   745.8  814.68
   774.9  814.51   784.6  813.59   813.8  807.77   872.1  806.23   901.3  812.77
   988.8  828.46  1066.5  850.75  1105.4  866.96  1115.1   869.6  1144.3  872.25
#Mann= 3 , 0 , 0
       0    .055       0   280.5    .045       0   295.5     .05       0
Bank Sta=280.5,295.5
XS Rating Curve= 0 ,0
Exp/Cntr=0.3,0.1

Type RM Length L Ch R = 1 ,4084.3  ,462.9,426.9,357
XS GIS Cut Line= 4
     1569038.656      285803.376     1568913.016      285993.036
     1568840.398      286093.785     1568672.141      286336.008
#Sta/Elev= 30
       0  897.98    75.8     862   180.1  810.85   189.6  806.57   199.1  803.04
     218  799.06     237  796.99   303.7  794.32   313.5  794.31   318.7  794.53
     323  794.71   351.7  800.35   361.5  801.42     391  810.02   400.8  812.22
   410.7  813.28   420.5  813.44   430.3  814.61   440.2  818.09   479.5  839.72
   489.3  844.67   499.2  848.91   518.8  855.58   528.6   858.5   538.5  860.67
   548.3  862.22     568  863.67   617.1  862.82   636.8  863.77   646.6  864.85
#Mann= 3 , 0 , 0
       0    .055       0   303.7    .045       0   318.7     .05       0
Bank Sta=303.7,318.7
XS Rating Curve= 0 ,0
Exp/Cntr=0.3,0.1

Type RM Length L Ch R = 1 ,3657.3  ,57.4,64.1,104.4
XS GIS Cut Line= 4
     1568461.638      285502.674     1568492.353      285740.073
     1568570.478      285839.031     1568624.398       286216.65
#Sta/Elev= 30
       0  858.08    38.3  851.01    86.2  839.55   105.3  835.63   172.4  826.03
   181.9  824.25   201.1  819.08   239.4  806.28   258.8     804   287.9  791.75
   297.6     790     317  790.69   336.4  791.09   365.5  792.84     385  797.92
   394.8  799.32   453.5   801.8   512.2  808.56   541.5  809.87   551.3  810.73
   561.1  813.22   570.8  817.55   600.2  832.96     610  837.09   619.8  840.36
   649.1  846.82   678.4  855.03     698  859.98   717.6   863.7   746.9  867.73
#Mann= 3 , 0 , 0
       0     .06       0   297.6    .045       0     317     .06       0
Bank Sta=297.6,317
XS Rating Curve= 0 ,0
Exp/Cntr=0.3,0.1

Type RM Length L Ch R = 1 ,3593.2  ,228.2,256.5,284.2
XS GIS Cut Line= 4
     1568394.364      285509.185     1568439.936        285747.9
     1568513.186      285846.844     1568557.124      286188.438
#Sta/Elev= 30
       0   846.7    58.3  836.49    87.5  830.47   106.9  825.33   145.8  811.41
   165.3  805.55   184.7  802.51   223.6  800.64     262  797.35   271.4  795.88
   287.4  790.79   290.4  789.74   299.8  789.58   302.4  790.22   309.3  791.93
   318.8  796.49   328.2  800.02   337.7  800.68   366.1  800.38   415.3  802.79
   454.7  807.62   494.1  809.01   503.9  810.53   513.7  814.34   543.3  831.43
   562.9  840.96   582.6  848.85   592.5  851.69   612.1  854.79   710.5  864.78
#Mann= 3 , 0 , 0
       0     .07       0   287.4    .045       0   302.4     .06       0
Bank Sta=287.4,302.4
XS Rating Curve= 0 ,0
Exp/Cntr=0.3,0.1

Type RM Length L Ch R = 1 ,3336.8  ,171.2,144.5,114.3
XS GIS Cut Line= 4
      1568406.59      285435.502      1568331.43      285559.098
     1568251.134      285689.306     1568141.441      285880.915
#Sta/Elev= 30
       0  858.98     9.6  858.52    28.9  855.38    67.5  845.09    96.4  835.96
   106.1  832.22   115.7  827.38     135  814.89   144.6  809.54   154.2  806.33
   173.3  804.76   182.9  803.04     202  797.88   225.3  789.51   230.7  788.03
   240.3  788.46     269  793.89   288.1  796.04   307.2  797.27   316.8     800
     336  807.14   345.6  808.91   364.8  810.23   374.4  814.86     384  822.08
   393.6  827.53   403.2  830.71   451.2  841.89   470.4  844.96   518.4  846.38
#Mann= 3 , 0 , 0
       0      .1       0   225.3    .045       0   240.3     .07       0
Bank Sta=225.3,240.3
XS Rating Curve= 0 ,0
Exp/Cntr=0.3,0.1

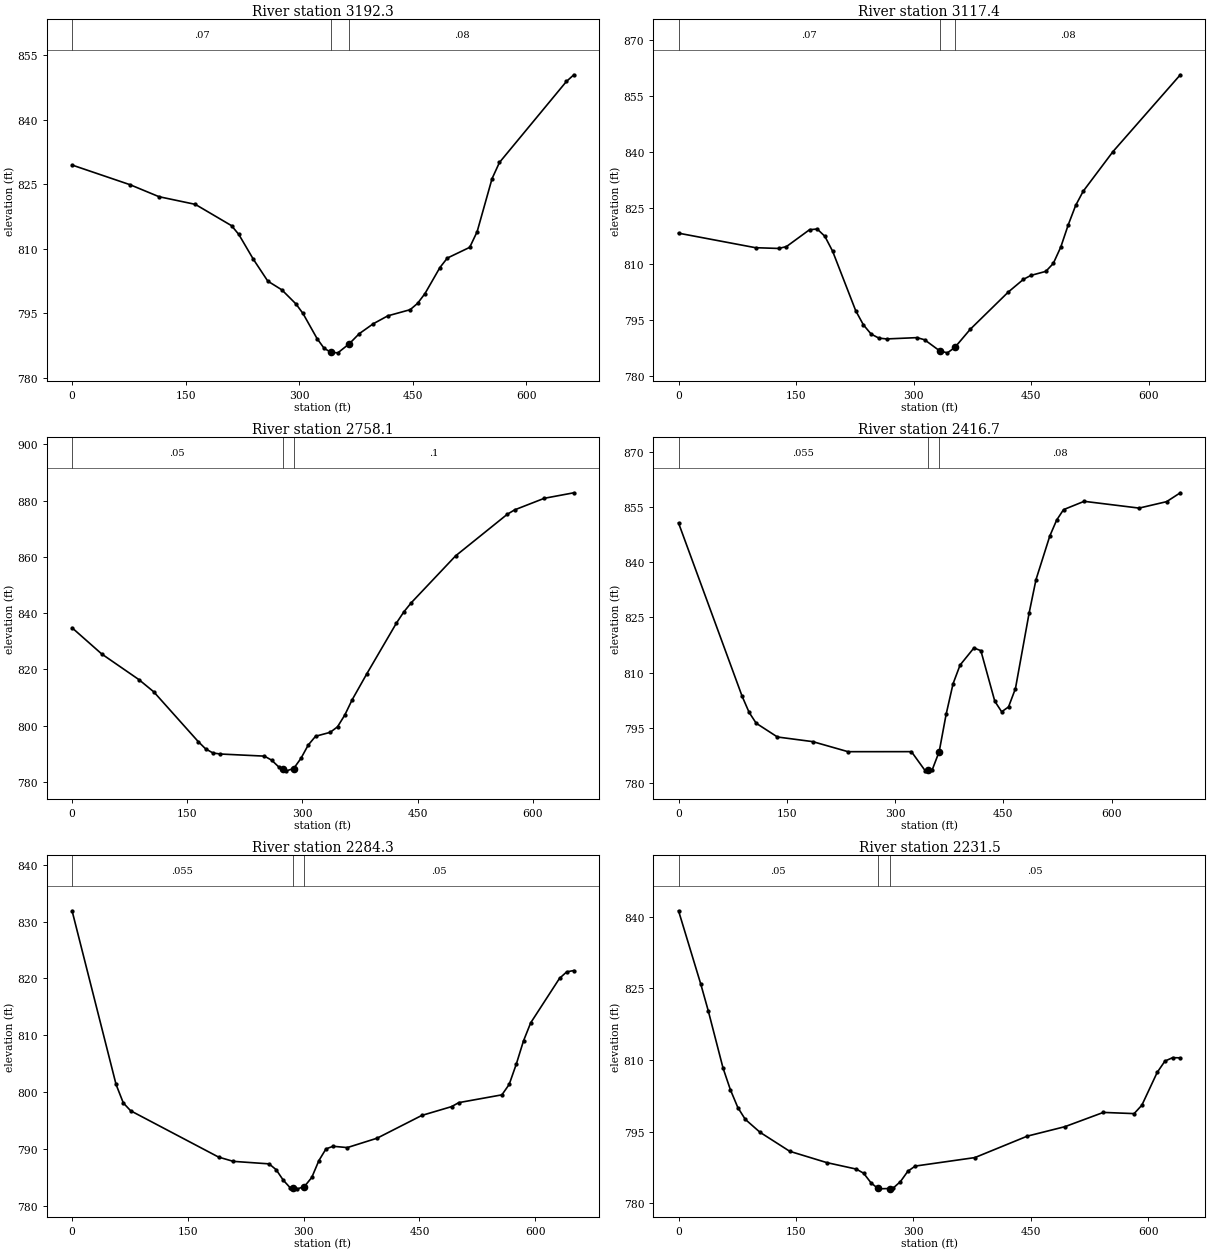
Type RM Length L Ch R = 1 ,3192.3  ,67.1,74.8,86.9
XS GIS Cut Line= 4
     1568219.957      285191.259     1568151.424      285440.594
     1568191.571      285583.823     1568138.837       285834.04
#Sta/Elev= 30
       0  829.51    76.6  824.93   114.9  822.14   162.8  820.36   210.7   815.4
   220.3  813.36   239.4  807.62   258.6   802.5   277.2  800.46   295.8  797.19
   305.1  794.97   323.7  789.13     333  786.87   342.2  785.92   351.2  785.81
   366.2  787.91   379.4  790.26     398  792.58   417.2  794.42   446.7  795.85
   456.5  797.32   466.3   799.6     486  805.65   495.8  807.86   525.4  810.36
   535.2     814   554.9  826.34   564.7  830.11   653.2  848.96     663  850.51
#Mann= 3 , 0 , 0
       0     .07       0   342.2    .045       0   366.2     .08       0
Bank Sta=342.2,366.2
XS Rating Curve= 0 ,0
Exp/Cntr=0.3,0.1

Type RM Length L Ch R = 1 ,3117.4  ,322.1,359.4,395.2
XS GIS Cut Line= 4
      1568169.61      285175.634     1568097.055       285431.06
     1568125.266       285593.82     1568075.035      285797.582
#Sta/Elev= 30
       0  818.26    98.3  814.36   127.8  814.16   137.7  814.65   167.2  819.18
     177  819.38   186.8  817.42   196.7  813.42   226.2  797.45     236  793.66
   245.9  791.18   255.7  790.11   265.5  789.88   304.4  790.23   314.1  789.66
   333.6  786.65   343.3  786.15   352.7  787.59   372.4  792.47     421  802.47
   440.3  805.87   449.8  806.92   468.9  808.01   478.4  810.13     488  814.54
   497.5  820.49     507  825.71   516.6  829.51   554.7  840.17   640.6  860.76
#Mann= 3 , 0 , 0
       0     .07       0   333.6    .045       0   352.7     .08       0
Bank Sta=333.6,352.7
XS Rating Curve= 0 ,0
Exp/Cntr=0.3,0.1

Type RM Length L Ch R = 1 ,2758.1  ,330,341.3,352.3
XS GIS Cut Line= 4
     1568249.037      285134.836     1568049.384      285171.294
     1567891.398      285206.016     1567667.439      285388.308
#Sta/Elev= 30
       0  834.81    38.7  825.48      87  816.39   106.3  812.06   164.3  794.34
     174  791.74   183.6  790.28   193.3  789.92   250.5  789.17     260  787.72
   269.6  785.21   274.2   784.6   279.1  783.94   288.6  784.76   298.1  788.39
   307.6  793.13   317.1  796.23   336.2  797.64   345.7   799.6   355.2  803.79
   364.7  809.18     384  818.52   422.5  836.52   432.1  840.47   441.7   843.7
   499.5  860.39   566.8  875.18   576.5  876.76     615  880.86   653.5  882.82
#Mann= 3 , 0 , 0
       0     .05       0   274.2    .045       0   288.6      .1       0
Bank Sta=274.2,288.6
XS Rating Curve= 0 ,0
Exp/Cntr=0.3,0.1

Type RM Length L Ch R = 1 ,2416.7  ,105.7,132.4,157.5
XS GIS Cut Line= 4
     1568350.165      284946.468     1568058.498      284863.134
      1567928.29      284828.412     1567671.346      284821.468
#Sta/Elev= 30
       0  850.66    88.1   803.6    97.8  799.22   107.6  796.28     137  792.55
   185.9  791.29   234.8  788.56   322.6  788.57   341.8  783.36  346.12783.4967
   351.5  783.67   361.1  788.61   370.7  798.73   380.3  807.02     390  812.08
   409.2  816.73   418.8  815.99   438.1  802.26   447.6   799.4   457.1  800.71
   466.7   805.7   485.7  826.26   495.2   835.3   514.3  847.13   523.8  851.45
   533.3  854.28   561.9  856.54     638   854.7   676.1  856.45   695.1  858.86
#Mann= 3 , 0 , 0
       0    .055       0  346.12    .045       0   361.1     .08       0
Bank Sta=346.12,361.1
XS Rating Curve= 0 ,0
Exp/Cntr=0.3,0.1

Type RM Length L Ch R = 1 ,2284.3  ,56.2,52.8,50.7
XS GIS Cut Line= 5
     1568324.123      284894.384     1568114.965       284831.87
     1568087.188      284696.453     1567989.965      284602.703
      1567840.66      284549.752
#Sta/Elev= 30
       0   831.9      57  801.37    66.4  798.12    75.9  796.75   189.8  788.61
   208.8  787.86   255.2  787.42   264.4  786.39   273.6  784.55   282.8  783.18
   285.9  783.13     292  783.03   300.9  783.43   310.5  785.03   319.7  787.99
   328.9  790.05   338.1  790.51   356.5  790.28   395.1  791.93     453  795.93
   491.6  797.48   500.9  798.18   556.8  799.55   566.2  801.38   575.5  804.98
   584.8  809.05   594.1  812.21   631.4  820.02   640.7  821.16     650   821.4
#Mann= 3 , 0 , 0
       0    .055       0   285.9    .045       0   300.9     .05       0
Bank Sta=285.9,300.9
XS Rating Curve= 0 ,0
Exp/Cntr=0.3,0.1

Type RM Length L Ch R = 1 ,2231.5  ,309.1,272.6,235.8
XS GIS Cut Line= 6
     1568353.637      284835.357     1568160.929      284786.745
     1568127.118      284679.092     1568054.202      284603.571
     1567990.833      284560.168     1567850.165      284515.912
#Sta/Elev= 30
       0  841.29    28.4  825.92    37.9  820.36    56.8  808.34    66.2  803.78
    75.7  800.05    85.2  797.57   104.1  794.85     142  790.87   189.3   788.5
     227  787.14   236.4  786.27   245.8  784.26   254.5  783.09   255.2     783
   269.5  783.07     274  783.14   283.4  784.52   292.8  786.68   302.2  787.77
   378.4  789.55   445.4  794.05   493.4  796.03   542.5  799.02   581.8  798.77
   591.7  800.54   611.3  807.42   621.2  809.79     631   810.5   640.8  810.46
#Mann= 3 , 0 , 0
       0     .05       0   254.5    .045       0   269.5     .05       0
Bank Sta=254.5,269.5
XS Rating Curve= 0 ,0
Exp/Cntr=0.3,0.1

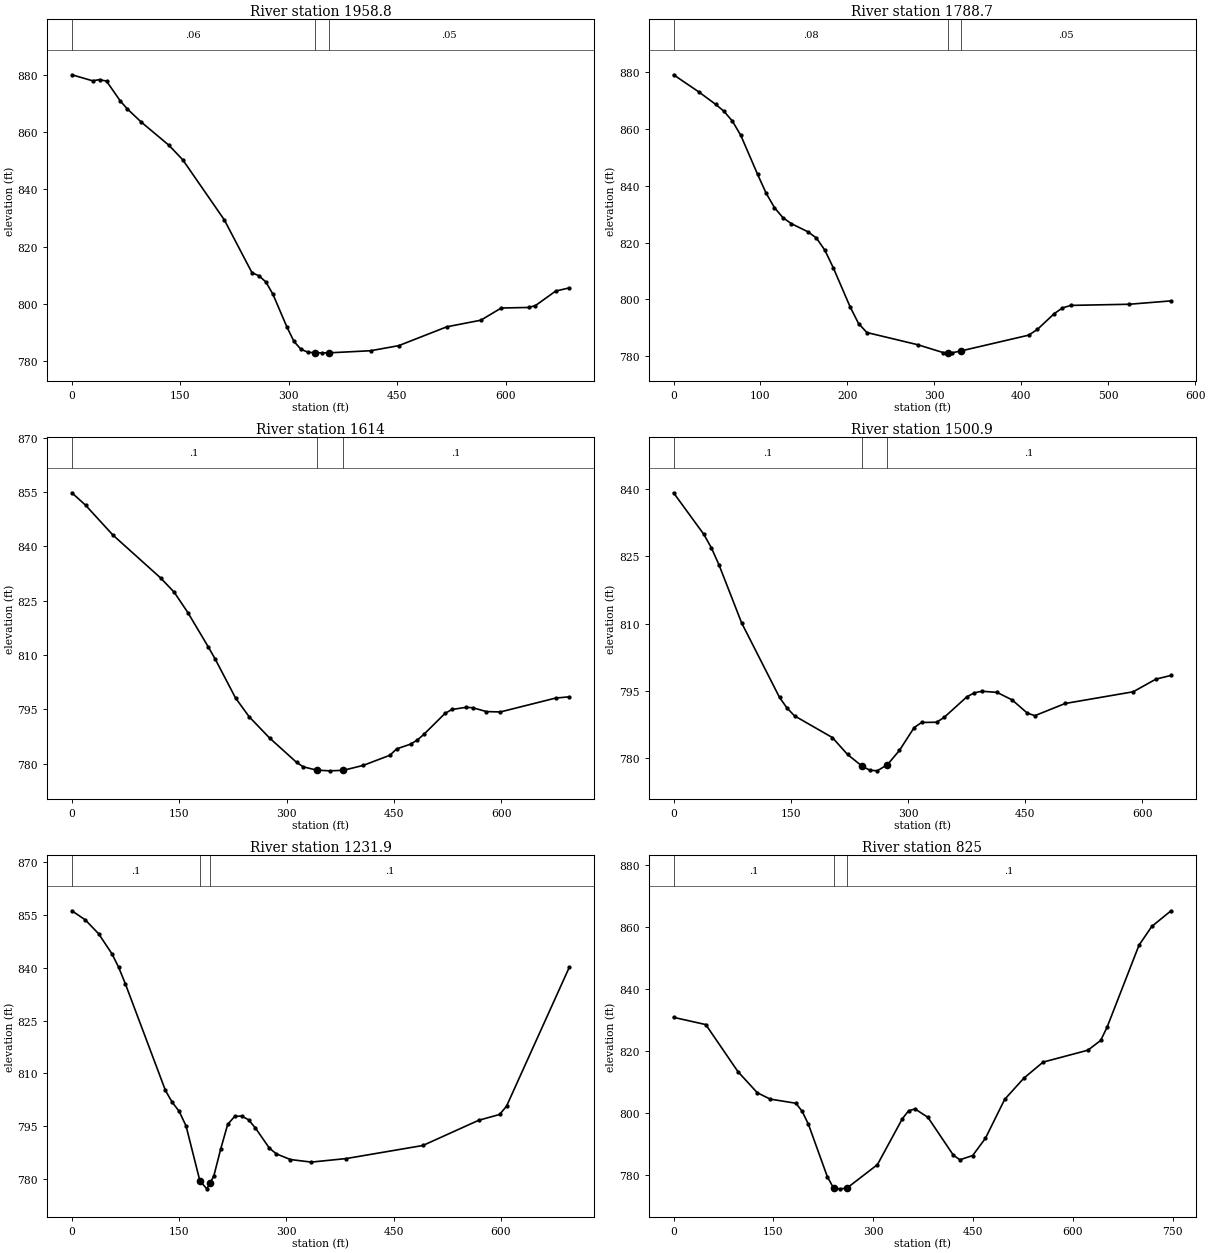
Type RM Length L Ch R = 1 ,1958.8  ,174.2,170.1,165.8
XS GIS Cut Line= 4
     1568476.901       284614.87     1568273.776      284470.773
     1568055.026      284547.162     1567853.247      284501.141
#Sta/Elev= 30
       0  879.94    28.7  877.84    38.3  878.25    47.9  877.73      67   870.8
    76.6  868.06    95.8  863.48   134.1  855.39   153.3  850.31   210.7  829.38
     249  810.95   258.7  809.86   268.4  807.66     278   803.4   297.3  792.01
     307     787   316.6  784.26   326.3  783.21   335.9  783.02   345.6     783
   355.8     783   413.2  783.74   451.8   785.5   518.4  792.08   565.4  794.38
   593.6  798.63   631.3  798.82   640.7  799.44   668.9  804.54   687.7  805.65
#Mann= 3 , 0 , 0
       0     .06       0   335.9    .045       0   355.8     .05       0
Bank Sta=335.9,355.8
XS Rating Curve= 0 ,0
Exp/Cntr=0.3,0.1

Type RM Length L Ch R = 1 ,1788.7  ,228.3,174.7,99.5
XS GIS Cut Line= 4
     1568367.526      284260.704     1568129.679      284342.301
     1567983.846      284423.898      1567834.54      284460.357
#Sta/Elev= 30
       0  879.12      29   873.1    48.4  868.71      58  866.27    67.7   862.8
    77.4  857.74    96.7  844.04   106.4  837.48   116.1  832.32   125.7  828.84
   135.4   826.7   154.7  823.81   164.4  821.61   174.1  817.32   183.8  811.12
   203.1   797.4   212.8  791.52   222.4  788.34   280.9  784.05   310.4  781.26
   315.6  781.22   320.3  781.19   330.6  781.86   408.7  787.43   418.6  789.45
   437.8  794.96   447.4     797     457   797.9   524.2   798.3   572.3  799.49
#Mann= 3 , 0 , 0
       0     .08       0   315.6    .045       0   330.6     .05       0
Bank Sta=315.6,330.6
XS Rating Curve= 0 ,0
Exp/Cntr=0.3,0.1

Type RM Length L Ch R = 1 ,1614    ,97.8,113.1,154
XS GIS Cut Line= 4
     1568072.387      283852.718     1568030.721      284135.704
     1568020.304       284293.69     1567810.235      284430.843
#Sta/Elev= 30
       0  854.79    19.1  851.38    57.2  843.15     124  831.28     143  827.34
   162.1  821.72   190.7  812.21   200.2  808.92   228.8  798.11   247.9  792.92
   276.5  787.04     314  780.36   323.3  779.13   341.9  778.21   360.5  778.01
   379.2  778.15   407.1  779.51   444.4  782.31     454  784.08   473.3  785.38
     483  786.53   492.6  788.21   521.6  793.89   531.2  794.95   550.5  795.54
   560.2  795.44   579.4  794.37   598.8  794.27     676   798.1   695.2  798.45
#Mann= 3 , 0 , 0
       0      .1       0   341.9    .045       0   379.2      .1       0
Bank Sta=341.9,379.2
XS Rating Curve= 0 ,0
Exp/Cntr=0.3,0.1

Type RM Length L Ch R = 1 ,1500.9  ,231.7,269,301
XS GIS Cut Line= 4
     1568001.207      283850.982     1567969.957      284071.468
     1567975.165      284175.634     1567766.832      284404.801
#Sta/Elev= 30
       0  839.15    38.7   829.9    48.4  826.89    58.1  823.12    87.1  810.18
   135.6  793.58   145.2  791.21   154.9  789.46   203.3  784.63   222.7  780.86
   241.6  778.22   251.1  777.37   260.6  777.22   273.7  778.59   289.1  781.77
     308  786.87   317.5  787.99   336.7  788.05   346.3  789.12   375.4  793.71
   385.1   794.6   394.7  794.95   414.1  794.69   433.4  793.01   452.8  790.07
   462.5  789.51   501.2  792.22   588.3  794.83   617.3  797.64   636.7  798.47
#Mann= 3 , 0 , 0
       0      .1       0   241.6    .045       0   273.7      .1       0
Bank Sta=241.6,273.7
XS Rating Curve= 0 ,0
Exp/Cntr=0.3,0.1

Type RM Length L Ch R = 1 ,1231.9  ,407.7,406.9,404.5
XS GIS Cut Line= 4
     1568011.623       283762.44     1567898.776      283845.773
     1567801.554      283910.009     1567463.012      284189.523
#Sta/Elev= 30
       0   856.2    18.7  853.63    37.4  849.68    56.1  843.97    65.5  840.12
    74.8  835.46   130.9  805.14   140.3   801.8     150  799.24   159.7  795.07
   179.1  779.43   188.8  777.18  193.22778.8186   198.5  780.78   208.3  788.58
     218  795.51   227.7  797.75   237.4  797.88   247.1  796.81   256.8  794.45
   276.3  788.74   286.1  787.11   305.6  785.51   334.9  784.78   383.6  785.78
     491   789.5     569  796.66   598.3  798.31     608  800.68   695.8  840.16
#Mann= 3 , 0 , 0
       0      .1       0   179.1    .045       0  193.22      .1       0
#XS Ineff= 2 , 0
                          227.51          797.46
Permanent Ineff=
       F       F
Bank Sta=179.1,193.22
XS Rating Curve= 0 ,0
Exp/Cntr=0.3,0.1

Type RM Length L Ch R = 1 ,825     ,401,398.8,395.9
XS GIS Cut Line= 4
     1567922.833      283513.146      1567740.79      283486.398
     1567607.806      283591.394     1567287.665      283821.468
#Sta/Elev= 30
       0  830.87    48.4  828.55    96.8   813.4   125.9  806.61   145.3  804.57
     184  803.23   193.4   800.6   202.8  796.41   231.1  779.62   240.5  775.95
   249.9   775.7  260.36775.9031   306.4  783.48     344   798.3   353.4  800.84
     363   801.4   382.3   798.7   420.7  786.48   430.4  785.05   449.6  786.42
   468.8  791.99   497.7  804.49   526.5  811.31   555.4  816.47   622.7   820.3
   641.9  823.43   651.5  827.65   699.6   854.1   718.8  860.13   747.7  865.16
#Mann= 3 , 0 , 0
       0      .1       0   240.5    .045       0  260.36      .1       0
Bank Sta=240.5,260.36
XS Rating Curve= 0 ,0
Exp/Cntr=0.3,0.1

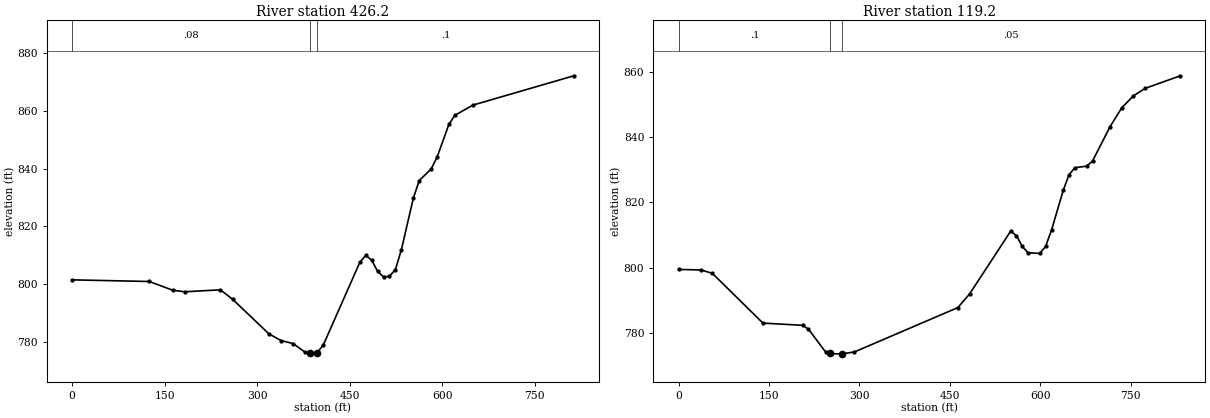
Type RM Length L Ch R = 1 ,426.2   ,301.8,306.9,311.8
XS GIS Cut Line= 4
     1567676.554      283054.107     1567487.318      283186.051
     1567320.651      283352.718     1567159.193      283660.009
#Sta/Elev= 30
       0   801.4     125  800.83   163.4  797.79   182.6  797.26   240.5  797.94
   260.2  794.68   319.1  782.67   338.7  780.34   358.4   779.3     378  776.25
     385  775.88   387.8  775.73   397.6  776.16   407.5  778.89   466.4  807.42
     476  809.92   485.7  808.24   495.3  804.37     505  802.39   514.6  802.65
   524.2  804.97   533.9  811.86   553.2  829.68   562.8  835.85   582.1  839.85
   591.8  843.96     611  855.42   620.7   858.5   649.6  862.01   813.5   872.2
#Mann= 3 , 0 , 0
       0     .08       0     385    .045       0   397.6      .1       0
Bank Sta=385,397.6
XS Rating Curve= 0 ,0
Exp/Cntr=0.3,0.1

Type RM Length L Ch R = 1 ,119.2   ,109.6,119.2,128.1
XS GIS Cut Line= 4
     1567389.228      282976.329     1567226.033      283045.773
     1567009.019      283182.926      1566776.38      283505.843
#Sta/Elev= 30
       0  799.45    37.3  799.29      56  798.26     140  783.01   205.9  782.34
   215.4  781.17   243.9  774.16  251.42773.7167   253.4   773.6   270.3  773.61
   291.4  774.16   463.2  787.77   482.6  791.93   550.6  811.13   560.3  809.83
     570  806.49   579.7  804.55   599.1  804.36   608.8  806.55   618.5  811.49
   637.9  823.67   647.6  828.48   657.3  830.61   676.8  831.08   686.5  832.66
   715.6  843.18     735  848.96   754.4  852.63   773.8  854.91   832.1  858.76
#Mann= 3 , 0 , 0
       0      .1       0  251.42    .045       0   270.3     .05       0
Bank Sta=251.42,270.3
XS Rating Curve= 0 ,0
Exp/Cntr=0.3,0.1

Chan Stop Cuts=-1
Use User Specified Reach Order=0
Composite Channel Slope=5